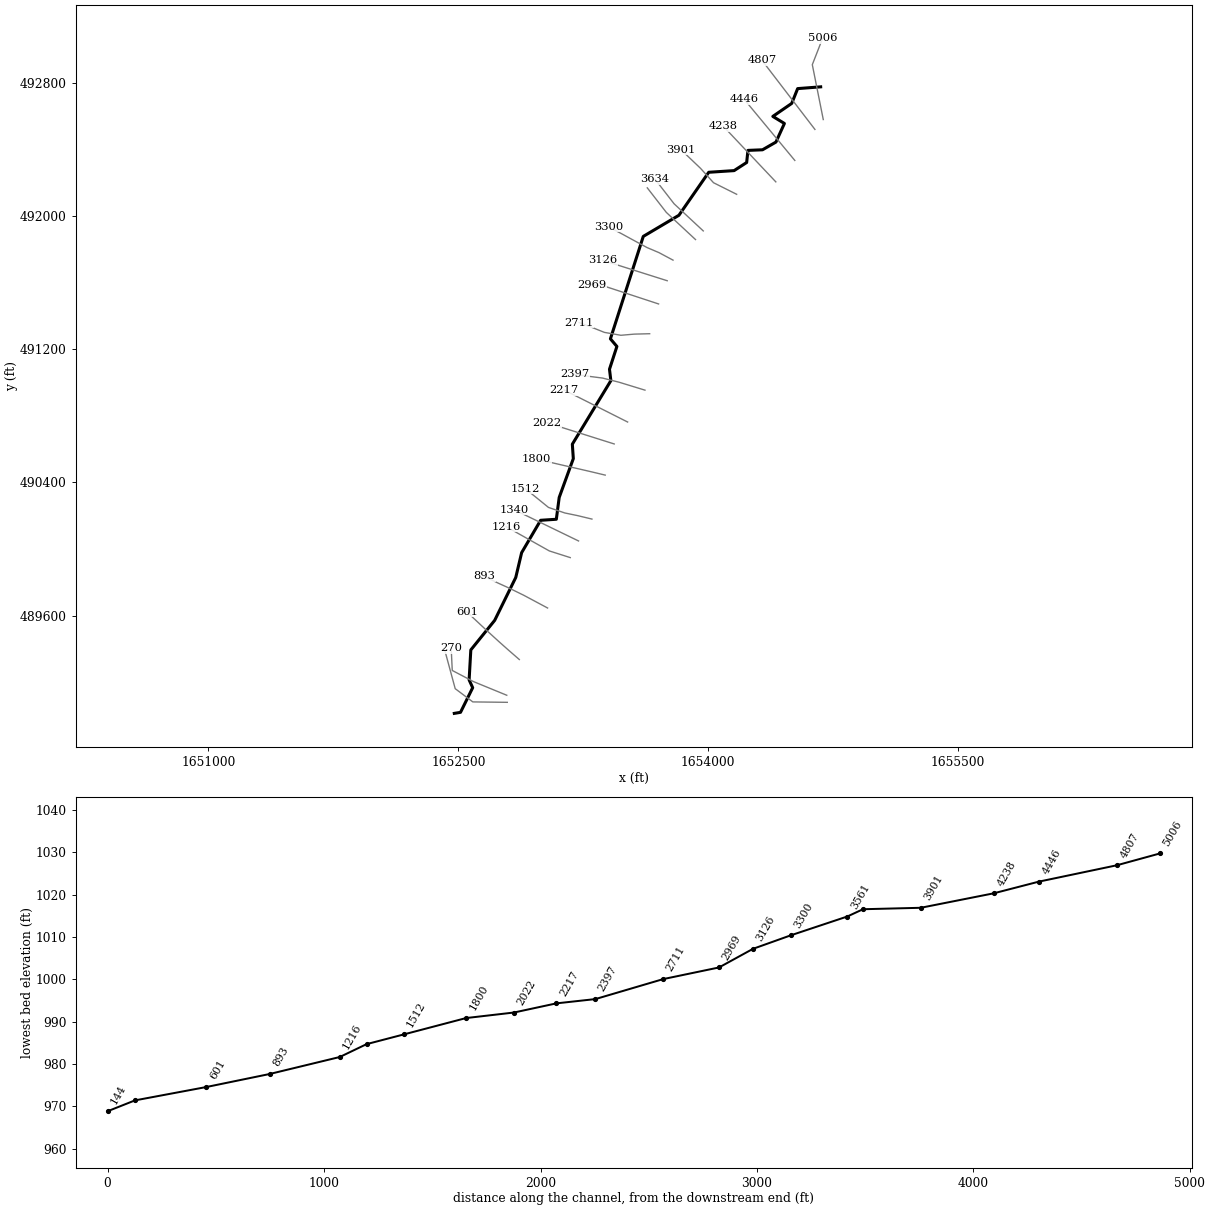
--- BurchRnII.prj (project) ---

Proj Title=BurchRnII
Current Plan=p01
Default Exp/Contr=0,0
English Units
Geom File=g01
Flow File=f01
Plan File=p01
BEGIN DESCRIPTION:
---------- MODELED AS PART OF WVEM CTP PROGRAM, 2025----------
Stream Name: Burch Run II
Flood Zone: AFH
Marshall County, WV
HEC-RAS Version: RAS 6.6
Vertical Datum: NAVD88
Projection: NAD 1983 StatePlane West Virginia N FIPS 4701 (US Feet)
Terrain: 1-meter West Virginia FEMA R3 South Central (collected 2018-2019)
Land Use: 2024 NLCD
Hydrologic Method:
Duda et al., "Estimation of magnitude and frequency of floods for rural, unregulated streams in and near Virginia and West Virginia." September 8, 2025.
Additional Model Notes:
None
END DESCRIPTION:
DSS Export Rating Curves= 0
DSS Export Rating Curve Sorted= 0
DSS Export Volume Flow Curves= 0
DXF OffsetX= 0
DXF OffsetY= 0
DXF ScaleX= 0
DXF ScaleY= 0

--- BurchRnII.p01 (plan) ---

Plan Title=Floodplain
Program Version=6.60
Short Identifier=Floodplain
Geom File=g01
Flow File=f01
Subcritical Flow
K Sum by GR= 0
Std Step Tol= 0.01
Critical Tol= 0.01
Num of Std Step Trials= 20
Max Error Tol= 0.3
Flow Tol Ratio= 0.001
Split Flow NTrial= 30
Split Flow Tol= 0.02
Split Flow Ratio= 0.02
Log Output Level= 0
Friction Slope Method= 1
Unsteady Friction Slope Method= 2
Unsteady Bridges Friction Slope Method= 1
Parabolic Critical Depth
Global Vel Dist= 0 , 0 , 0
Global Log Level= 0
CheckData=False
Encroach Param=-1 ,0,0, 0
Flow Ratio Tolerance=0.1
Flow Ratio Min Ratio=0.5
Flow Ratio Max Ratio=4
Flow Ratio Max Iterations= 10
Mapping Interval=1HOUR
Computation Time Step Use Courant=        0
Computation Time Step Use Time Series=    0
Computation Time Step Count To Double=0
Computation Time Step Max Doubling=0
Computation Time Step Max Halving=0
Computation Time Step Residence Courant=0
Run HTab= 0
Run UNet= 0
Run Sediment= 0
Run PostProcess= 0
Run WQNet= 0
Run RASMapper=-1
UNET Theta= 0
UNET Theta Warmup= 0
UNET ZTol= 0
UNET ZSATol= 0
UNET MxIter= 0
UNET Max Iter WO Improvement= 0
UNET MaxInSteps= 0
UNET DtIC= 0
UNET DtMin= 0
UNET MaxCRTS= 0
UNET WFStab= 0
UNET SFStab= 0
UNET WFX= 1
UNET SFX= 1
UNET Gravity=32.17405
UNET 1D Methodology=Finite Difference
UNET DSS MLevel= 1
UNET Pardiso=0
UNET DZMax Abort= 0
UNET Use Existing IB Tables= 0
UNET Froude Reduction=False
UNET Froude Limit= 0
UNET Froude Power= 0
UNET D1 Cores= 0
UNET WindReference=Eulerian
UNET WindDragFormulation=Hsu (1988)
UNET D2 Coriolis=0
UNET D2 Cores= 0
UNET D2 Theta= 1
UNET D2 Theta Warmup= 1
UNET D2 Z Tol= 0.01
UNET D2 Volume Tol= 0.01
UNET D2 Max Iterations= 20
UNET D2 Advanced Convergence=0
UNET D2 WS Max Tol=0.15
UNET D2 WS RMS Tol=0.002
UNET D2 WS Stall Tol=1
UNET D2 Equation= 0
UNET D2 RampUpFraction=0.1
UNET D2 TimeSlices= 1
UNET D2 Turbulence Formulation=Non-Conservative (original)
UNET D2 Eddy Viscosity=0.3
UNET D2 Transverse Eddy Viscosity=0.1
UNET D2 Smagorinsky Mixing=0
UNET D2 BCVolumeCheck=0
UNET D2 Cores=0
UNET D2 SolverType=PARDISO (Direct)
UNET D2 Minimum Iterations= 3
UNET D2 Maximum Iterations= 30
UNET D2 Restart Number= 10
UNET D2 Relaxation Coeff=1.3
UNET D2 SOR Precondition Iterations= 10
UNET D2 ILUT Maximum Fill= 8
UNET D2 ILUT Tolerance=1E-08
UNET D2 Convergence Tolerance=0.00001
PS Theta= 1
PS WS Tol= 0.01
PS Volume Tol= 0.01
PS Max Iterations= 20
PS Equation= 0
PS Advance Time Step=-1
PS Target Courant=0.9
PS Time Slices= 1
PS Iterate With 2D=0
PS Project Initial WSE from DS=-1
PS Ramp Up Initial WSE from US=-1
PS Cores=0
UNET D1D2 MaxIter= 0
UNET D1D2 ZTol=0.01
UNET D1D2 QTol=0.1
UNET D1D2 MinQTol=1
Write IC File= 0
Write IC File at Fixed DateTime=0
Write IC File at Sim End=0
Echo Input=False
Echo Parameters=False
Echo Output=False
Write Detailed= 0
HDF Write Warmup=0
HDF Write Time Slices=0
HDF Flush=0
HDF Compression= 1
HDF Chunk Size= 1
HDF Spatial Parts= 1
HDF Use Max Rows=0
HDF Fixed Rows= 1
Calibration Method= 0
Calibration Iterations= 20
Calibration Max Change=0.05
Calibration Tolerance=0.2
Calibration Maximum=1.5
Calibration Minimum=0.5
Calibration Optimization Method= 1
WQ AD Non Conservative
WQ ULTIMATE=-1
WQ Max Comp Step=1HOUR
WQ Output Interval=15MIN
WQ Output Selected Increments= 0
WQ Create Restart=0
WQ Fixed Restart=0
WQ System Summary=0
WQ Write To DSS=0
Sorting and Armoring Iterations= 10
XS Update Threshold= 0.02
Bed Roughness Predictor= 0
Processes Affected by Predictor=Sediment Only
Hydraulics Update Threshold= 0.02
Energy Slope Method= 1
Volume Change Method= 1
Sediment Retention Method= 0
Sediment TS Multiplier= 1
Warm Up Method= 0
XS Weighting Method= 0
Number of US Weighted Cross Sections= 1
Number of DS Weighted Cross Sections= 1
Upstream XS Weight=0
Main XS Weight=1
Downstream XS Weight=0
Number of DS XS's Weighted with US Boundary= 1
Upstream Boundary Weight= 1
Weight of XSs Associated with US Boundary= 0
Number of US XS's Weighted with DS Boundary= 1
Downstream Boundary Weight= 0.5
Weight of XSs Associated with DS Boundary= 0.5
Percentile Method= 0
Sediment Output Level= 3
Mass or Volume Output= 0
Output Increment Type= 1
Profile and TS Output Increment= 1
Transport Output Increment 1
XS Output Flag= 0
XS Output Increment= 10
Read HDF5 Sediment Hotstart= 0
Sediment Hotstart Type= 0
Write Gradation File= 0
Read Gradation Hotstart= 0
Write HDF5 File= 1
Write Binary Output= 1
Write DSS Sediment File= 0
DSS Sediment Output Type= 1
SV Curve= 0
Specific Gage Flag= 0
Subcell Erosion Methods= 0
Subcell Deposition Methods= 0
Advection Scheme= 1
Matrix Solver= 0
Implicit Weighting Factor= 1
Maximum Outer Loop Convergence Iterations= 5
Convergence Maximum Absolute= 0.001
Convergence RMSE= 0.0001
Grain Fractions Max Abs Error= 0.001
Max Subgrid Regions= 1
Max Subgrid Length Scale= 3.402823E+38
Initial Layer Thickness= 3
Min Layer Thickness= 0.1
Max Layer Thickness= 6
Number of Layers= 5

--- BurchRnII.f01 (steady flow) ---

Flow Title=Flow
Program Version=6.60
Number of Profiles= 1
Profile Names=P100yr
River Rch & RM=BurchRnII,Main            ,5006
     903
Boundary for River Rch & Prof#=BurchRnII,Main            , 1
Up Type= 0
Dn Type= 3
Dn Slope=0.020183
DSS Import GetInterval= 0
DSS Import GetPeak= 0
DSS Import FillOption= 0

--- BurchRnII.g01 (geometry) ---

Geom Title=Geometry
Program Version=6.60

River Reach=BurchRnII       ,Main
Reach XY= 30
1654675.09574288492775.757747999     1654536.971      492765.204
     1654501.395      492676.403     1654387.885      492598.238
     1654457.441       492555.87      1654406.59      492444.082
     1654326.023      492397.772      1654238.53      492394.222
     1654230.799      492321.475     1654155.479      492272.738
     1654003.176      492262.766 1653824.1446179 492004.57487778
     1653610.215      491877.759     1653412.912      491262.635
     1653451.795      491216.829       1653407.3      491079.988
     1653415.559      491011.473     1653184.323      490629.881
     1653190.189      490543.358     1653105.425      490310.186
     1653088.191      490179.163      1652993.99      490173.022
     1652879.879      489978.465     1652844.632      489829.631
     1652718.116      489572.138     1652574.811      489394.515
     1652564.663      489214.657     1652586.022        489167.6
     1652513.015      489019.794     1652475.691      489013.541

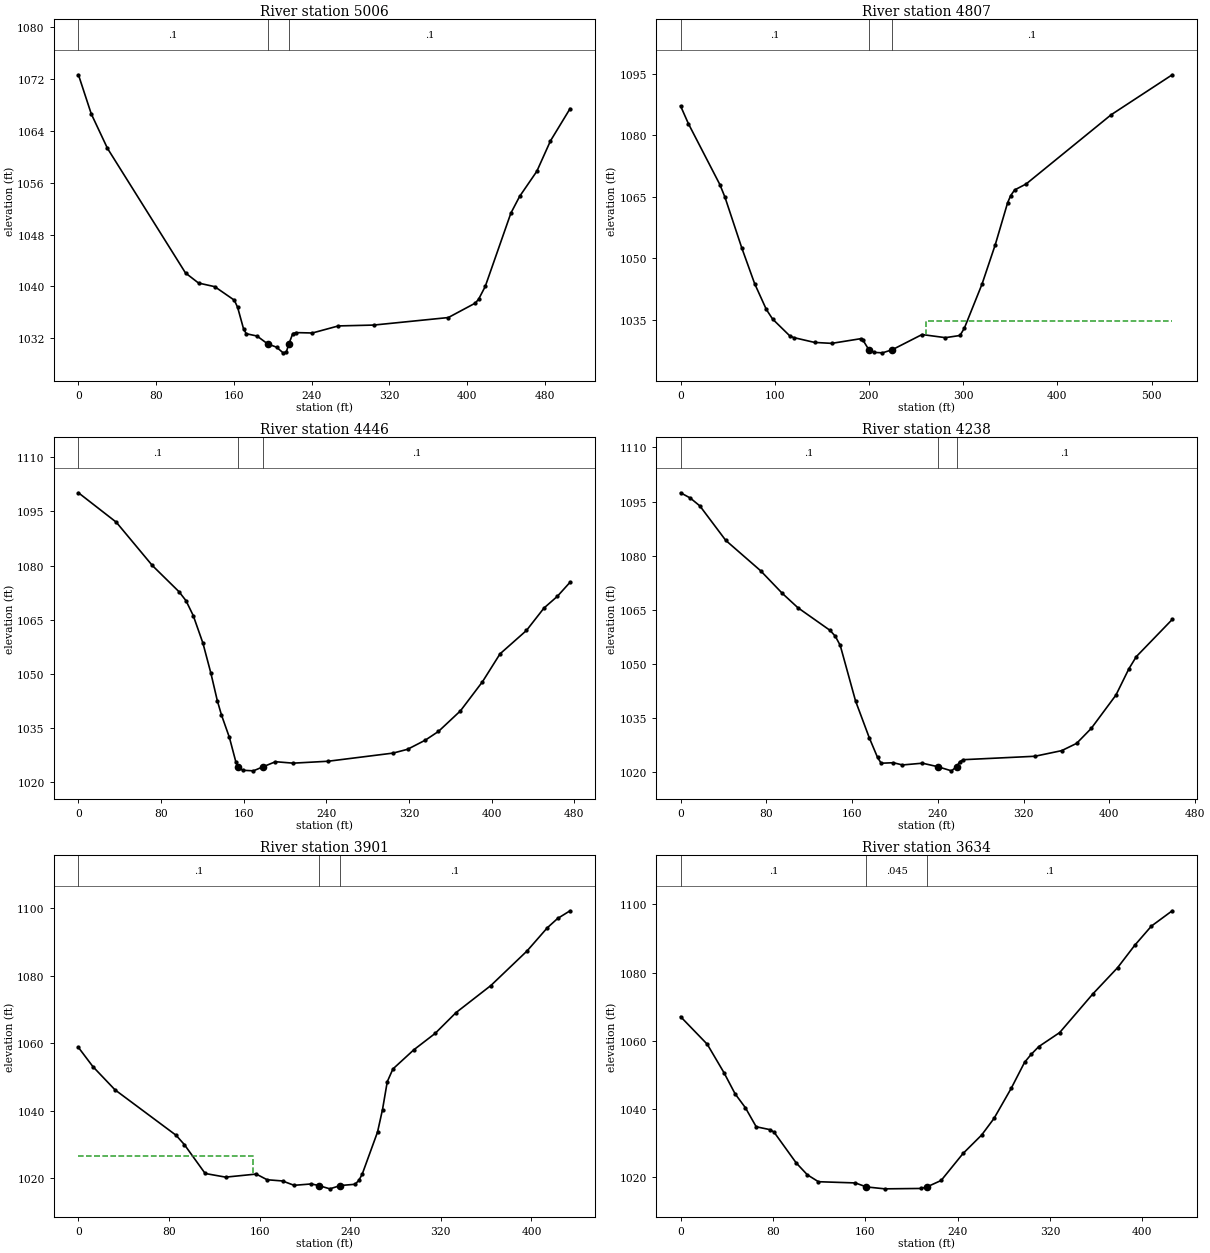
Type RM Length L Ch R = 1 ,5006    ,187.7,199.7,200.6
XS GIS Cut Line= 3
1654690.75577509492579.3251784291654624.93791661492908.898080572
1654686.68064995 493067.06458429
#Sta/Elev= 30
       0 1072.63    13.2  1066.6    29.9 1061.28   110.2 1042.07   123.6 1040.52
   140.3 1039.96   160.4 1037.88   163.8 1036.78   169.9 1033.46   172.7 1032.71
   183.8 1032.35  194.651031.146   203.9 1030.63   210.6 1029.76   213.9 1029.89
  216.571031.148   220.6 1032.74     224 1032.88   240.7 1032.82   267.5 1033.91
   303.8 1034.04   380.6  1035.2   408.3 1037.42   411.8 1038.03   418.6 1039.99
     445  1051.3     454 1053.88   471.7 1057.75   485.7 1062.43   505.9 1067.41
#Mann= 3 ,-1,0
       0      .1       0  194.65    .045       0  216.57      .1       0
Bank Sta=194.65,216.57
XS Rating Curve= 0 ,0
Exp/Cntr(USF)=0,0
Exp/Cntr=0.3,0.1

Type RM Length L Ch R = 1 ,4807    ,346,360.7,348.1
XS GIS Cut Line= 2
1654640.68589708492520.0441011841654323.30352138492934.337125952
#Sta/Elev= 30
       0 1087.13     8.3 1082.81    41.7 1067.97    47.1  1064.9    64.9 1052.57
    78.6 1043.83      91 1037.54    97.7 1035.19   115.8 1031.12   119.9 1030.69
   142.2  1029.5   160.4 1029.27   191.3 1030.41   193.6 1030.05  199.831027.722
   205.3 1027.07   214.3 1026.96  224.741027.722   256.3 1031.42   281.1 1030.66
   296.6 1031.19   301.3 1033.01     320 1043.72   334.1 1053.36   347.2 1063.58
   350.4 1065.28   354.6 1066.67   366.8 1068.12   457.1    1085   521.9 1094.74
#Mann= 3 ,-1,0
       0      .1       0  199.83    .045       0  224.74      .1       0
#XS Ineff= 2 , 0
                          260.36         1034.75
Permanent Ineff=
       F       F
Bank Sta=199.83,224.74
XS Rating Curve= 0 ,0
Exp/Cntr(USF)=0,0
Exp/Cntr=0.3,0.1

Type RM Length L Ch R = 1 ,4446    ,203.8,207.9,204.5
XS GIS Cut Line= 2
1654519.90133812492333.8284299251654216.43259219492700.257055238
#Sta/Elev= 30
       0 1100.19    36.6 1092.04    71.5 1080.03    97.3 1072.77   104.1 1070.27
   111.1 1066.15   120.5 1058.48   128.2 1050.15   134.4 1042.55   138.4 1038.61
   146.1 1032.35   152.4 1025.51  154.351024.226     159 1023.25   169.3 1023.09
  178.781024.226   190.7 1025.62   207.8 1025.22   241.6 1025.75   304.5 1028.01
   318.5 1029.06   335.6 1031.58   348.4 1034.01   369.7 1039.72     391 1047.78
     408 1055.52   433.6 1062.01   450.6 1068.24   463.4 1071.45   475.8 1075.38
#Mann= 3 ,-1,0
       0      .1       0  154.35    .045       0  178.78      .1       0
Bank Sta=154.35,178.78
XS Rating Curve= 0 ,0
Exp/Cntr(USF)=0,0
Exp/Cntr=0.3,0.1

Type RM Length L Ch R = 1 ,4238    ,335.1,337.5,337.1
XS GIS Cut Line= 2
1654405.87497776492205.150268358 1654091.0288318 492538.60947118
#Sta/Elev= 30
       0 1097.42       9 1095.97      18 1093.77    42.1 1084.23    74.6 1075.82
    94.8 1069.56   109.4 1065.56   139.4 1059.28   144.3 1057.66   148.9 1055.12
   163.2 1039.71     176 1029.51   183.7 1024.07   187.1 1022.45   198.5 1022.59
   206.9 1021.97   225.6 1022.46  239.661021.503   252.7 1020.34  257.461021.502
   260.3 1022.83   263.6 1023.43   330.5 1024.38   355.5 1025.94   369.4 1027.95
   383.1 1032.12   406.1 1041.34   418.1 1048.59   425.1    1052   458.6  1062.3
#Mann= 3 ,-1,0
       0      .1       0  239.66    .045       0  257.46      .1       0
Bank Sta=239.66,257.46
XS Rating Curve= 0 ,0
Exp/Cntr(USF)=0,0
Exp/Cntr=0.3,0.1

Type RM Length L Ch R = 1 ,3901    ,266.3,266.7,264.2
XS GIS Cut Line= 5
1654170.75605156492130.5733735661654031.89497591492200.028116851
1653953.90718317492286.4058167491653899.65499508492338.190818176
1653836.36050226492398.606707841
#Sta/Elev= 30
       0 1058.74    12.8 1053.06    32.3  1046.2    86.2 1032.77    93.5 1030.02
   111.9 1021.46     130 1020.38     157 1021.29   166.6 1019.61   180.2 1019.25
   190.4 1017.96   205.7 1018.37   212.1  1017.9     222 1016.92   231.3  1017.9
   244.2 1018.27   247.6 1019.42   250.6 1021.29   264.1 1033.72   268.5 1040.38
   272.7 1048.61   277.7 1052.38   296.1 1058.03   314.9 1062.87   333.4 1069.04
   364.2 1077.06   396.1 1087.27     414 1094.13   423.1 1096.88   434.1 1099.16
#Mann= 3 ,-1,0
       0      .1       0   212.1    .045       0   231.3      .1       0
#XS Ineff= 2 , 0
          153.79 1026.68
Permanent Ineff=
       F       F
Bank Sta=212.1,231.3
XS Rating Curve= 0 ,0
Exp/Cntr(USF)=0,0
Exp/Cntr=0.3,0.1

Type RM Length L Ch R = 1 ,3634    ,72.3,72.6,76
XS GIS Cut Line= 3
1653970.33692897491910.5255857721653795.11663694492073.601227222
1653680.80776913492221.004281161
#Sta/Elev= 30
       0 1067.06    23.1 1058.97    37.6 1050.63    47.2 1044.45    56.2 1040.33
    65.5 1034.78    77.1 1033.96    80.9 1033.23   100.2 1024.16   109.8  1020.7
   119.4 1018.67   151.4 1018.31  160.931017.145   176.9 1016.58     208 1016.69
  213.381017.145   225.7 1019.03   244.7 1026.95   260.8 1032.36   271.5 1037.22
   286.4 1046.04     298 1053.68   303.6 1055.97   310.3 1058.29   328.4  1062.4
   357.1 1073.72   378.6 1081.44   393.4 1087.98   407.9 1093.63   425.9 1098.11
#Mann= 3 ,-1,0
       0      .1       0  160.93    .045       0  213.38      .1       0
Bank Sta=160.93,213.38
XS Rating Curve= 0 ,0
Exp/Cntr(USF)=0,0
Exp/Cntr=0.3,0.1

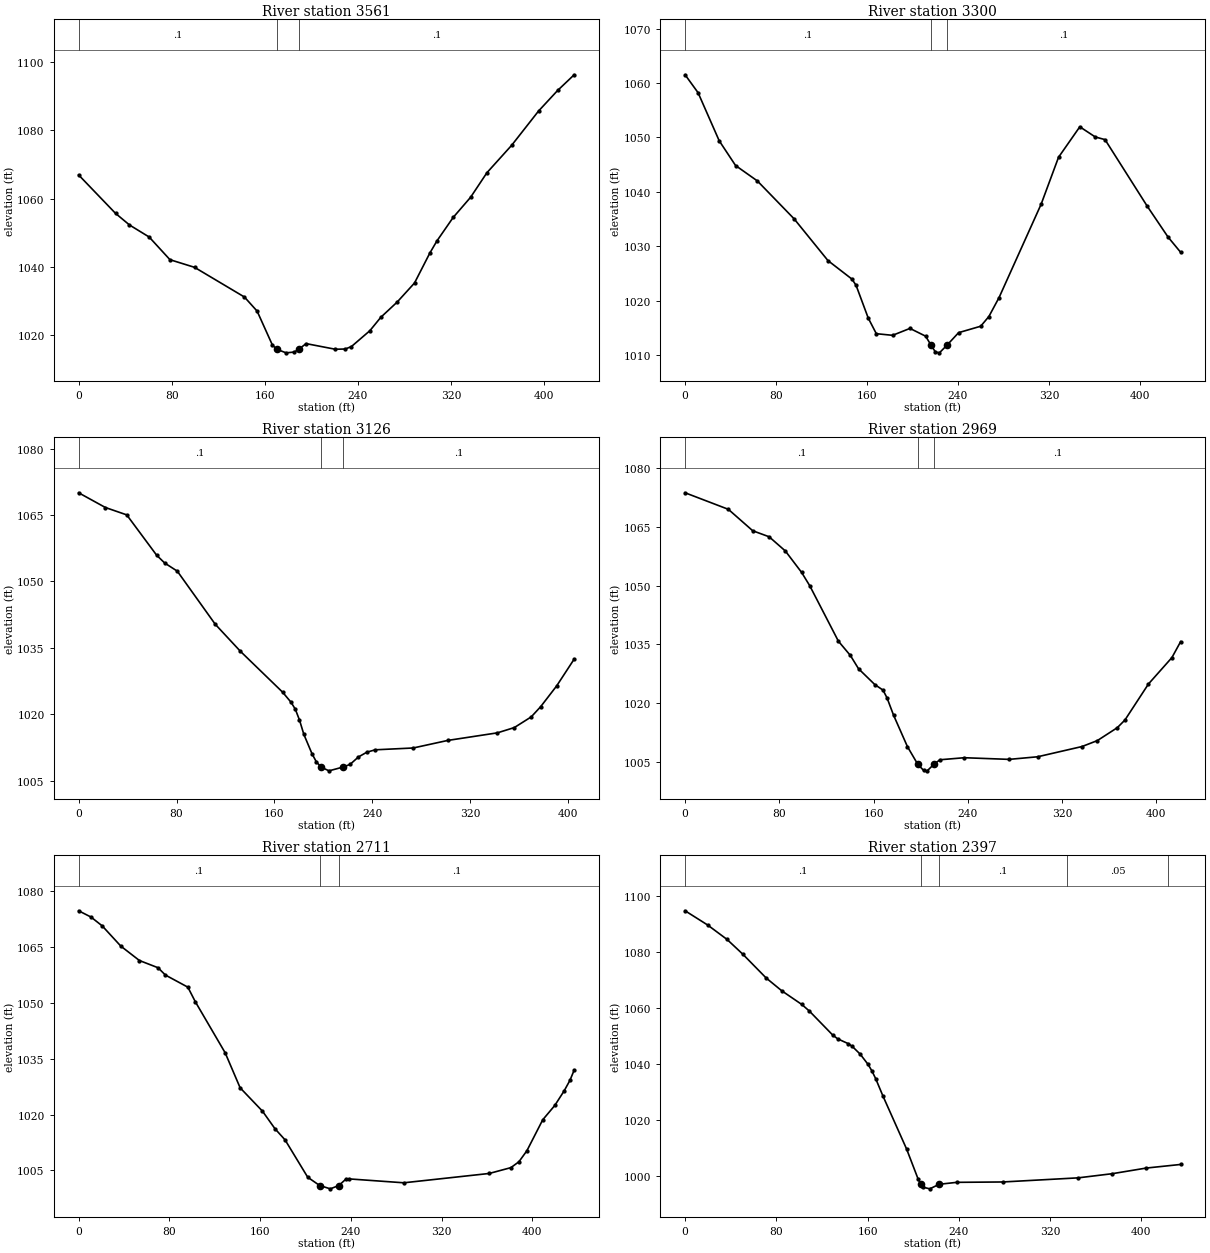
Type RM Length L Ch R = 1 ,3561    ,260.2,261.4,262.6
XS GIS Cut Line= 3
1653923.78568712491858.7234065851653748.56539509492021.799048035
1653634.25652728492169.202101974
#Sta/Elev= 30
       0  1066.9    31.7 1055.67    43.7 1052.27    60.6 1048.75    78.5 1042.11
    99.6 1039.88   142.5 1031.19   153.4 1027.07   166.6 1017.09  170.641015.856
   178.3 1014.86   185.3 1015.09  189.02 1015.86   195.5 1017.56   220.6 1015.91
   229.2 1015.98   234.5 1016.71   250.3 1021.33   259.7 1025.25   273.7 1029.69
   288.7  1035.3   301.8 1044.02   307.9 1047.58   321.9 1054.47   336.9 1060.38
   350.9 1067.55   372.2 1075.59   395.3 1085.61   411.7 1091.63   425.9 1096.21
#Mann= 3 ,-1,0
       0      .1       0  170.64    .045       0  189.02      .1       0
Bank Sta=170.64,189.02
XS Rating Curve= 0 ,0
Exp/Cntr(USF)=0,0
Exp/Cntr=0.3,0.1

Type RM Length L Ch R = 1 ,3300    ,171.2,174.1,172.8
XS GIS Cut Line= 6
 1653788.7631565491735.2130215021653704.20197393491780.360240921
1653632.89568609491810.6803902541653544.96574384491858.307591587
1653479.12958942491894.2366535961653401.59792034491934.913409501
#Sta/Elev= 30
       0 1061.52    11.4 1058.23      30 1049.39    44.4 1044.84    63.5 1042.02
    95.9 1035.04   125.7 1027.36   146.8 1023.96   150.4 1022.82   161.1  1016.8
   168.2 1013.93   182.5 1013.63   197.8  1014.9   211.6 1013.47  216.38  1011.8
   220.2 1010.57   223.7 1010.41  230.271011.798   240.6 1014.12     260  1015.3
   267.2 1017.08   276.2 1020.58   313.2 1037.74   328.5 1046.36   347.2 1051.96
   360.8 1050.09   369.4  1049.6   406.5 1037.37   424.8  1031.7   435.9 1028.89
#Mann= 3 ,-1,0
       0      .1       0  216.38    .045       0  230.27      .1       0
Bank Sta=216.38,230.27
XS Rating Curve= 0 ,0
Exp/Cntr(USF)=0,0
Exp/Cntr=0.3,0.1

Type RM Length L Ch R = 1 ,3126    ,155.6,157.1,155.4
XS GIS Cut Line= 2
1653753.86384703491611.4967551181653367.91718712491733.604172945
#Sta/Elev= 30
       0 1070.02    21.9 1066.69    39.3 1065.03    63.7 1055.93    70.3 1054.16
    80.6 1052.32   111.6 1040.33   132.2 1034.21   166.6    1025   173.5 1022.72
     177 1021.15   180.4 1018.71     184 1015.45   190.7 1011.05   194.2 1009.26
  197.961008.093   204.5 1007.23  216.091008.093   221.7 1008.68   228.6 1010.37
   235.5 1011.45   242.3 1011.98   273.3 1012.39   301.6  1014.1   342.1 1015.81
   355.9    1017   369.7 1019.41   377.4 1021.71   390.5 1026.41   404.8 1032.46
#Mann= 3 ,-1,0
       0      .1       0  197.96    .045       0  216.09      .1       0
Bank Sta=197.96,216.09
XS Rating Curve= 0 ,0
Exp/Cntr(USF)=0,0
Exp/Cntr=0.3,0.1

Type RM Length L Ch R = 1 ,2969    ,255.9,257.9,258.5
XS GIS Cut Line= 3
1653702.05381495491472.0966831381653388.09532267491575.302252084
1653299.01183942491588.712658346
#Sta/Elev= 30
       0 1073.63    36.7 1069.42    57.4 1063.96    71.3 1062.43    85.1 1058.81
    98.9 1053.35   105.8 1049.96   130.1 1035.85   140.3  1032.2   147.2 1028.83
     161  1024.8     168 1023.38   171.4  1021.4   176.9 1017.03   188.7    1009
  197.421004.528   202.5 1002.92   205.5 1002.83  211.261004.527   216.3 1005.65
     237 1006.17     275 1005.75   299.2 1006.41   336.9 1009.02   349.9 1010.53
   366.8 1013.81   373.3 1015.76   393.3 1024.95   413.2 1031.67   420.6 1035.73
#Mann= 3 ,-1,0
       0      .1       0  197.42    .045       0  211.26      .1       0
Bank Sta=197.42,211.26
XS Rating Curve= 0 ,0
Exp/Cntr(USF)=0,0
Exp/Cntr=0.3,0.1

Type RM Length L Ch R = 1 ,2711    ,309.6,313.4,308.6
XS GIS Cut Line= 6
1653648.54854192491293.336608678 1653555.6927565491290.874015167
 1653475.7637825491283.9219293451653377.07828434491301.255228013
1653306.96982875 491329.283059091653224.64289367491360.609439999
#Sta/Elev= 30
       0 1074.59    10.9 1072.91    20.8 1070.54    37.2 1065.12    53.6 1061.26
      70 1059.33    76.5 1057.37    96.3 1054.12   102.8 1050.26   129.2 1036.53
   142.4 1027.15   162.1 1020.89   173.1 1016.19     182  1013.2     202 1003.18
  212.521000.973   221.9 1000.08   229.41000.973   235.3 1002.59   238.6 1002.74
   286.7  1001.7     362  1004.2   381.1 1005.76   388.2 1007.34   395.2 1010.28
   409.2 1018.59   419.8 1022.42   428.1 1026.35   433.2 1029.17   436.9  1031.9
#Mann= 3 ,-1,0
       0      .1       0  212.52    .045       0   229.4      .1       0
Bank Sta=212.52,229.4
XS Rating Curve= 0 ,0
Exp/Cntr(USF)=0,0
Exp/Cntr=0.3,0.1

Type RM Length L Ch R = 1 ,2397    ,181.3,180.1,177.7
XS GIS Cut Line= 6
1653620.34584242490954.4803310041653536.67803076490980.092156425
1653464.96295109491002.0455245821653366.03303084491026.946393415
1653287.69985418 491037.08384034 1653197.6619765491049.514261678
#Sta/Elev= 30
       0 1094.55    19.7 1089.49    36.8 1084.32    50.5  1079.1    71.1 1070.56
    84.8 1065.99   102.3 1061.13   108.9 1058.79   129.4 1050.22   133.8 1048.86
   143.2 1047.12   146.6 1046.15   153.5  1043.4   160.3  1039.8   163.7 1037.47
   167.1 1034.64   173.5 1028.41   194.2 1009.54   204.3  998.82   206.7996.9824
   207.7   996.2   208.7  995.94   214.5  995.36  222.69996.9814   238.2  997.68
   278.5  997.81   344.6  999.28   374.4 1000.76   404.2 1002.77   434.4 1004.06
#Mann= 5 ,-1,0
       0      .1       0   206.7    .045       0  222.69      .1       0
  334.52     .05       0   423.5      .1       0
Bank Sta=206.7,222.69
XS Rating Curve= 0 ,0
Exp/Cntr(USF)=0,0
Exp/Cntr=0.3,0.1

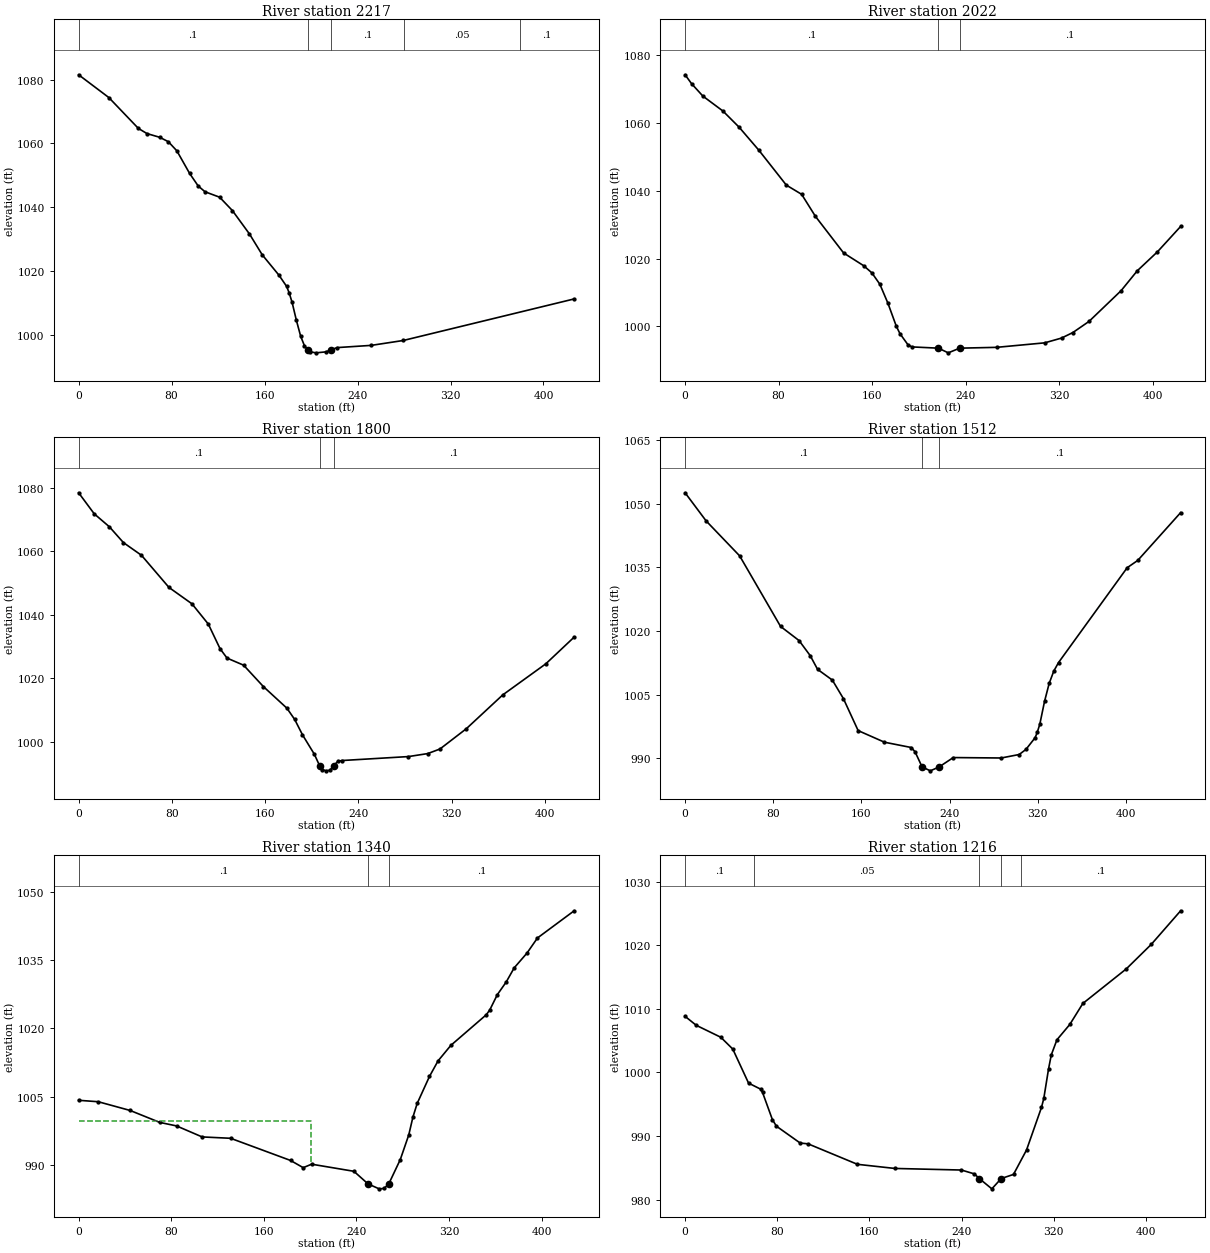
Type RM Length L Ch R = 1 ,2217    ,194.2,195.7,196.6
XS GIS Cut Line= 2
1653516.25377538490763.0274015371653135.50289645490955.054248452
#Sta/Elev= 30
       0 1081.51      26 1074.37    51.4  1064.7    58.8 1063.08    69.8 1061.91
    77.2 1060.53    84.5 1057.68    95.5 1050.59   102.9 1046.64   108.8 1044.83
   121.3 1043.14   132.3 1038.95     147 1031.61     158 1025.07   172.4 1018.68
     179 1015.16   181.2  1013.1   183.7 1010.15   187.4  1004.5   191.1   999.5
   194.3  996.59  196.96 995.356   199.2   994.7   204.1  994.35   213.1  994.66
  217.13995.3561   222.7     996   251.8  996.69   279.3  998.22   426.4 1011.25
#Mann= 5 ,-1,0
       0      .1       0  196.96    .045       0  217.13      .1       0
     280     .05       0     380      .1       0
Bank Sta=196.96,217.13
XS Rating Curve= 0 ,0
Exp/Cntr(USF)=0,0
Exp/Cntr=0.3,0.1

Type RM Length L Ch R = 1 ,2022    ,220.1,221.6,221.6
XS GIS Cut Line= 2
1653435.62644016490631.3694517361653031.36366757490758.928093573
#Sta/Elev= 30
       0 1074.27     5.5 1071.66    15.2 1067.98    32.4 1063.56    46.2  1058.8
    63.1    1052    86.6  1041.7    99.7 1038.98   111.5 1032.47   135.6 1021.67
   152.8  1017.9   159.8 1015.79   166.6 1012.44   173.5 1006.84   180.7 1000.03
   183.8  997.85   190.7  994.55   194.1  993.94  216.71  993.57   225.1  992.19
   234.9  993.57   266.4  993.81   307.6  995.14     322  996.55   331.7  998.18
   345.5 1001.46     373 1010.55   386.8 1016.41     404 1021.99   423.9  1029.5
#Mann= 3 ,-1,0
       0      .1       0  216.71    .045       0   234.9      .1       0
Bank Sta=216.71,234.9
XS Rating Curve= 0 ,0
Exp/Cntr(USF)=0,0
Exp/Cntr=0.3,0.1

Type RM Length L Ch R = 1 ,1800    ,286.7,288.1,285.2
XS GIS Cut Line= 6
1653381.67309143490444.2405378371653296.57582067490464.639447168
1653223.49886709490481.5623135861653126.03285468490503.931363344
1653052.97657034490520.8483242541652967.73756759490540.587129921
#Sta/Elev= 30
       0 1078.37    13.4 1071.74    26.4 1067.66    38.4  1062.7    53.9  1058.7
    77.5 1048.58    97.2 1043.43   111.2 1037.07   121.3  1029.3   127.3 1026.35
   141.5 1024.12   158.4 1017.41   178.6  1010.6   185.3 1007.05     192 1002.21
   202.1  996.14  206.63992.5414   208.9  991.29   212.2  990.88   215.6  991.07
  218.67992.5397   222.3  993.85   225.7  994.12   282.9  995.37   299.4  996.31
   309.9  997.75   332.5 1004.13   363.7 1014.76   400.7 1024.56     425 1032.96
#Mann= 3 ,-1,0
       0      .1       0  206.63    .045       0  218.67      .1       0
Bank Sta=206.63,218.67
XS Rating Curve= 0 ,0
Exp/Cntr(USF)=0,0
Exp/Cntr=0.3,0.1

Type RM Length L Ch R = 1 ,1512    ,167.4,171.5,168.4
XS GIS Cut Line= 6
1653301.92685984490180.3083229211653215.02217801490201.231837511
1653139.17062367490216.9594963341653041.12587225490250.231739506
1652975.99214426490303.1286153351652901.59301484490362.753496096
#Sta/Elev= 30
       0 1052.58    19.1 1045.94    49.5  1037.7    86.6 1021.07   103.4 1017.73
   113.5 1014.18   120.2 1010.94   133.6 1008.41   143.6 1004.06     157   996.5
   180.9  993.76   205.2  992.51   208.6  991.52  215.02987.9421   222.5  987.01
  230.53987.9404   243.3  990.14   286.8  990.04   303.1  990.86   309.2  992.05
   317.6  994.83   319.5  996.09   321.8  997.97   326.1 1003.37   330.3 1007.61
   334.5 1010.53   338.8 1012.54   401.1 1034.91   410.7 1036.63   449.6  1047.9
#Mann= 3 ,-1,0
       0      .1       0  215.02    .045       0  230.53      .1       0
Bank Sta=215.02,230.53
XS Rating Curve= 0 ,0
Exp/Cntr(USF)=0,0
Exp/Cntr=0.3,0.1

Type RM Length L Ch R = 1 ,1340    ,124.4,124,123.3
XS GIS Cut Line= 2
1653221.63454272490048.7989961951652836.46059242 490235.71052021
#Sta/Elev= 30
       0  1004.2      17 1003.88    44.5 1001.96      70  999.34    84.6  998.56
   106.7  996.14   131.3  995.84   183.1  990.96     194  989.38   201.3  990.14
   237.8  988.58     250  985.81   259.6  984.72   263.8   984.8  267.92   985.8
   277.9  991.17   285.2  996.58   288.8 1000.51   292.5 1003.52   303.1 1009.45
   310.5 1012.87   321.6 1016.29   352.2 1023.02   355.2 1024.08   361.7 1027.43
   369.4 1030.23   376.3 1033.34   387.3 1036.57   396.4 1039.91   428.1 1045.89
#Mann= 3 ,-1,0
       0      .1       0     250    .045       0  267.92      .1       0
#XS Ineff= 2 , 0
          200.72   999.6
Permanent Ineff=
       F       F
Bank Sta=250,267.92
XS Rating Curve= 0 ,0
Exp/Cntr(USF)=0,0
Exp/Cntr=0.3,0.1

Type RM Length L Ch R = 1 ,1216    ,322,323.9,323.1
XS GIS Cut Line= 4
1653171.81839495489948.9133924271653046.24372801489988.953769045
1652862.49886886490092.0999690361652786.11680379490135.124489284
#Sta/Elev= 30
       0 1008.83     9.7 1007.42      31 1005.54    41.4 1003.68    55.1  998.32
    65.5  997.38    67.2  996.87    75.8  992.57    79.3  991.54    99.9  988.89
   106.8  988.76   149.6  985.54   182.1  984.89   239.9  984.64   251.2  984.03
  255.39983.3024   266.3  981.68  274.42983.3016   285.1  983.95   296.4  987.79
   309.4   994.5   311.4  995.91   315.5 1000.53   317.9 1002.76   322.8 1005.14
     334 1007.56   345.3 1010.86     383  1016.3   404.7 1020.16   430.2 1025.45
#Mann= 5 ,-1,0
       0      .1       0      60     .05       0  255.39    .045       0
  274.42     .05       0   291.8      .1       0
Bank Sta=255.39,274.42
XS Rating Curve= 0 ,0
Exp/Cntr(USF)=0,0
Exp/Cntr=0.3,0.1

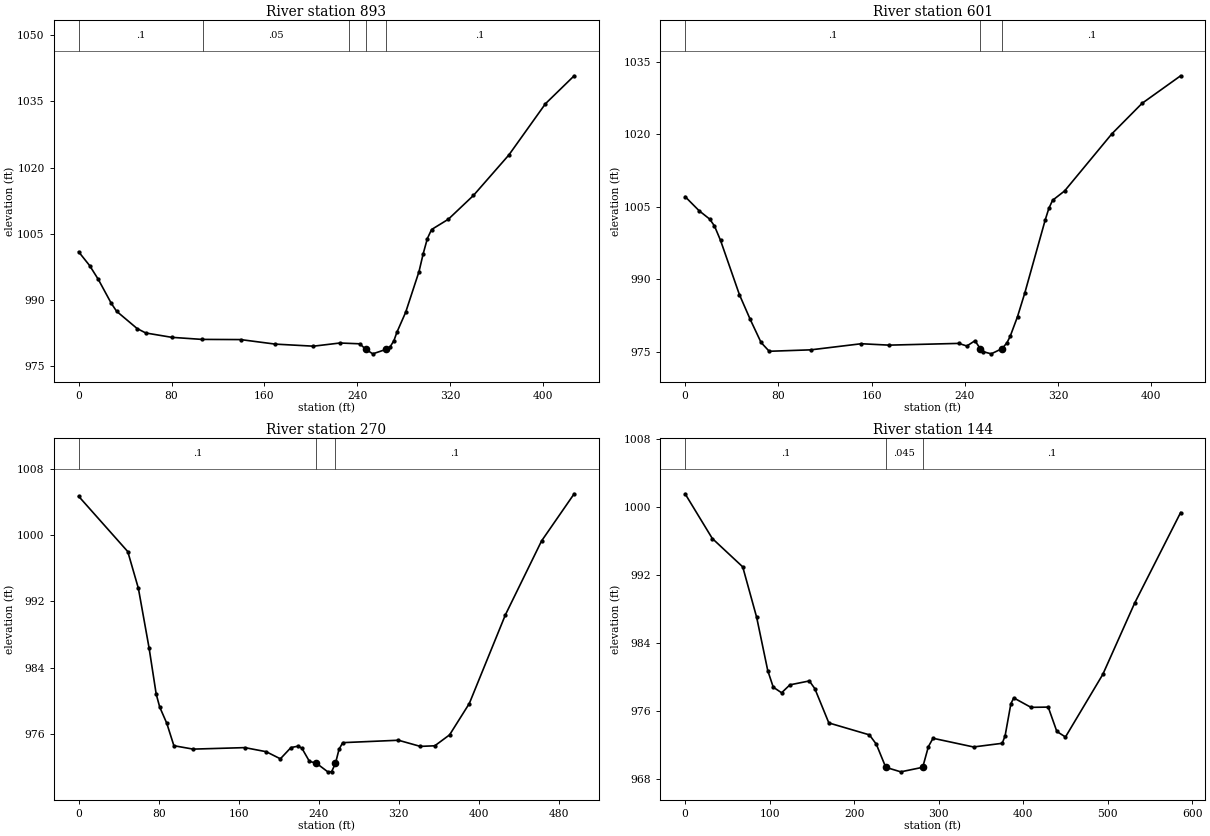
Type RM Length L Ch R = 1 ,893     ,294.3,291.9,288.6
XS GIS Cut Line= 6
1653035.77035907489646.2634323131652958.64321673489687.489399735
1652892.53311273489722.8265993931652802.47850282489766.889503393
1652733.48159356489798.2785482291652654.09494132489836.865085233
#Sta/Elev= 30
       0 1000.85     9.5  997.71    16.9   994.6    28.1  989.15    32.7  987.34
    50.4  983.41    57.8  982.41    80.2  981.42   106.2  980.95   139.4  980.91
   169.3  979.88   202.2  979.41     225  980.13   242.1  979.95  247.24978.7004
   253.3  977.67  264.87978.7012   267.9  979.12   271.5  980.67   274.1   982.6
   281.6  987.11   293.1  996.37   296.7 1000.42   300.3 1003.87   303.9 1005.91
   318.3 1008.24     340 1013.66   370.5 1022.86     402  1034.5   426.7 1040.84
#Mann= 5 ,-1,0
       0      .1       0  107.45     .05       0  232.42      .1       0
  247.24    .045       0  264.87      .1       0
Bank Sta=247.24,264.87
XS Rating Curve= 0 ,0
Exp/Cntr(USF)=0,0
Exp/Cntr=0.3,0.1

Type RM Length L Ch R = 1 ,601     ,326.4,330.2,331.2
XS GIS Cut Line= 6
 1652865.9813549489336.8784602021652799.78463691 489394.42329261
  1652743.647282489444.3480615351652669.72485765489511.768858451
1652615.01269674  489563.01186621652551.18342807489622.795539278
#Sta/Elev= 30
       0 1007.13    12.1 1004.19    21.1 1002.48    25.2 1001.06    30.4  998.08
    46.6  986.86    55.9  981.72    65.2  976.95    72.2  975.13     108  975.43
   151.2  976.69     175   976.4   234.9  976.76   241.8  976.22   248.8  977.31
  253.25  975.69   255.8  975.05   262.7   974.6  272.13 975.686   276.3  976.92
     279  978.22   285.3   982.3   291.5  987.15   309.1 1002.33   312.2  1004.7
   315.4 1006.37   325.7  1008.3   366.2  1020.1   392.2 1026.43   425.3 1032.13
#Mann= 3 ,-1,0
       0      .1       0  253.25    .045       0  272.13      .1       0
Bank Sta=253.25,272.13
XS Rating Curve= 0 ,0
Exp/Cntr(USF)=0,0
Exp/Cntr=0.3,0.1

Type RM Length L Ch R = 1 ,270     ,129.4,126.2,110.4
XS GIS Cut Line= 4
1652790.68088777 489122.333820831652590.81235849489204.385545801
1652463.40301869489271.2561035761652456.99023251 489406.36120041
#Sta/Elev= 30
       0 1004.67    49.1     998    59.7  993.57    70.4  986.38    77.5  980.82
      81  979.26    88.1  977.29    95.2  974.59   114.4  974.18   166.1  974.36
   187.4  973.87   201.6  973.01   212.2  974.37   219.5  974.54   223.2  974.27
   230.6  972.71237.6955972.4698     249  971.44   252.8  971.46  256.68  972.47
   260.2  974.15   263.9  974.96   319.6  975.25   341.4  974.51   355.9  974.58
   370.7   975.9   390.4  979.68   426.5  990.38   462.6  999.28   495.2 1004.97
#Mann= 3 ,0,0
       0      .1       0237.6955    .045       0  256.68      .1       0
Bank Sta=237.6955,256.68
XS Rating Curve= 0 ,0
Exp/Cntr(USF)=0,0
Exp/Cntr=0.3,0.1

Type RM Length L Ch R = 1 ,144     ,,,
XS GIS Cut Line= 4
1652793.82056108489079.8572021461652586.79893566489082.430081049
1652481.09207039489161.9089271161652416.41654048489400.444850916
#Sta/Elev= 30
       0 1001.52    32.2  996.27    68.2  992.94    84.7  987.01    97.8  980.77
   104.3  978.82   114.2  978.16     124  979.09     147  979.55   153.5  978.65
   170.1  974.62   218.1  973.22   226.3  972.12  237.45 969.412   255.2  968.88
  281.17969.4122   287.9  971.84   293.4  972.82   341.3   971.8   375.3  972.23
   378.7  973.12   385.5  976.87   388.9  977.56   409.3  976.45   429.7  976.48
   439.9  973.62   450.1  972.97   494.3  980.32     532  988.69   586.4  999.32
#Mann= 3 ,-1,0
       0      .1       0  237.45    .045       0  281.17      .1       0
Bank Sta=237.45,281.17
XS Rating Curve= 0 ,0
Exp/Cntr(USF)=0,0
Exp/Cntr=0.3,0.1
LCMann Table=0

Chan Stop Cuts=-1
Use User Specified Reach Order=0
Composite Channel Slope=5